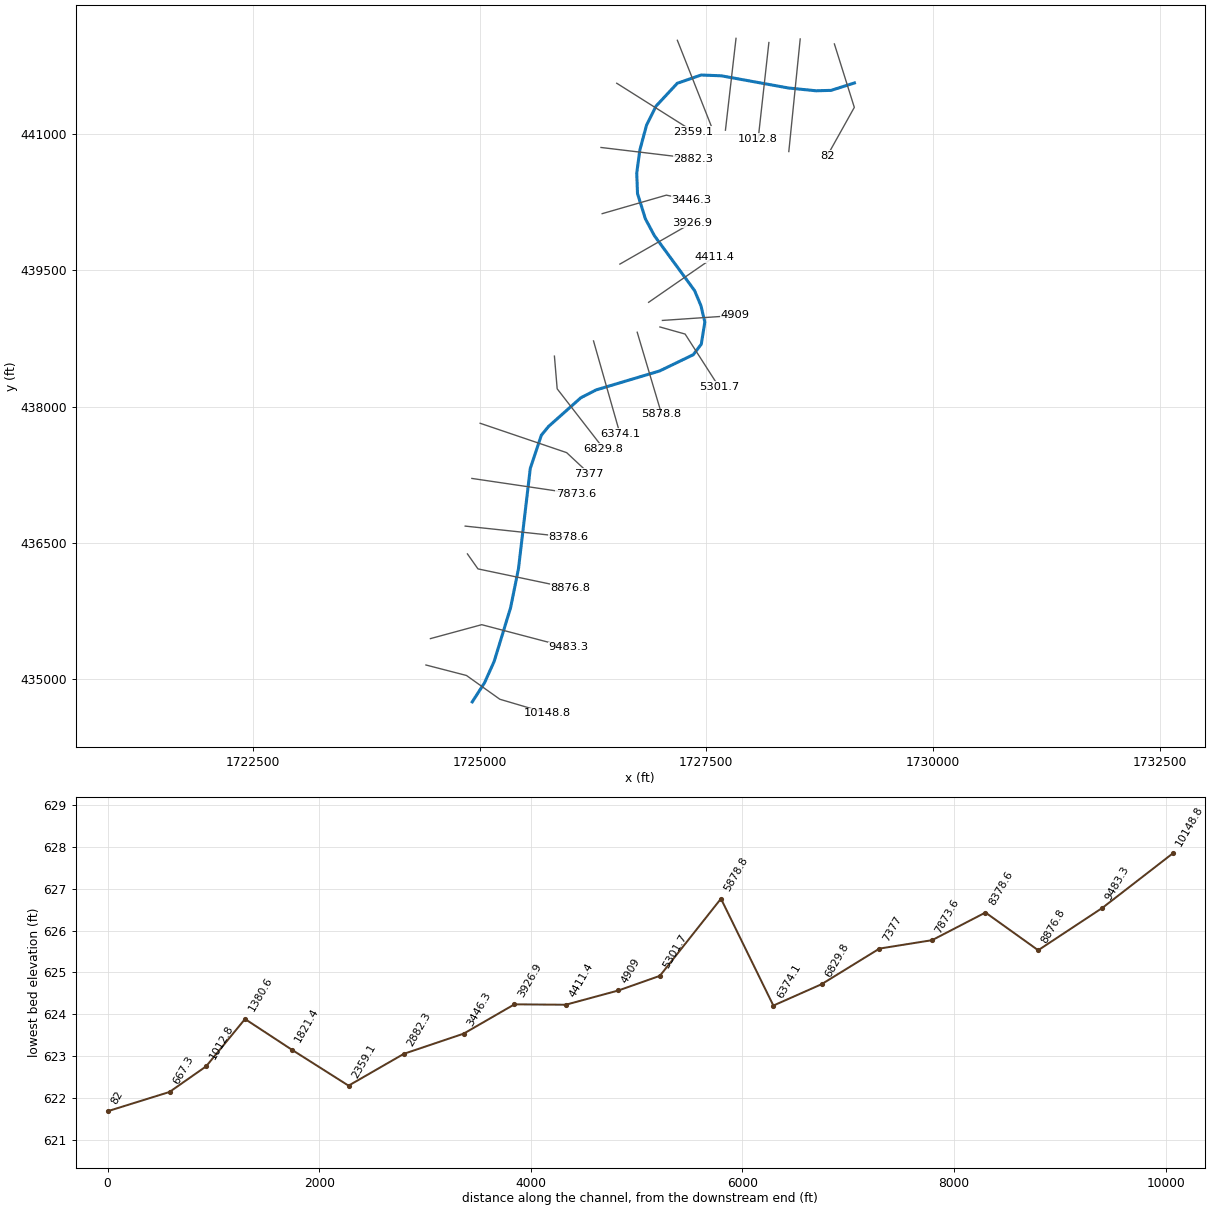
--- LITCOALRV.prj (project) ---

Proj Title=LITCOALRV
Current Plan=p01
Default Exp/Contr=0,0
English Units
Geom File=g01
Flow File=f01
Plan File=p01
BEGIN DESCRIPTION:
END DESCRIPTION:
DSS Export Rating Curves= 0
DSS Export Rating Curve Sorted= 0
DSS Export Volume Flow Curves= 0
DXF OffsetX= 0
DXF OffsetY= 0
DXF ScaleX= 0
DXF ScaleY= 0

--- LITCOALRV.p01 (plan) ---

Plan Title=Floodplain
Program Version=4.00
Geom File=g01
Flow File=f01
K Sum by GR=0
Std Step Tol=0.01
Critical Tol=0.01
Num of Std Step Trials=20
Max Error Tol=0.3
Flow Tol Ratio=0.001
Split Flow NTrial=30
Split Flow Tol=0.02
Split Flow Ratio=0.02
Log Output Level=0
Friction Slope Method=1
Unsteady Friction Slope Method=2
Unsteady Bridges Friction Slope Method=1
Global Log Level=0
CheckData=False
Run HTab=0
Run UNet=0
Run PostProcess=0
UNET Theta=0
UNET Theta Warmup=0
UNET ZTol=0
UNET ZSATol=0
UNET MxIter=0
UNET MaxInSteps=0
UNET DtIC=0
UNET DtMin=0
UNET MaxCRTS=0
UNET WFStab=0
UNET SFStab=0
UNET WFX=0
UNET SFX=0
UNET DSS MLevel=0
UNET DZMax Abort=0
UNET Convert EG Bridges=0
UNET Use Existing IB Tables=0
UNET Froude Limit=0
UNET Froude Power=0
Write IC File=0
Echo Input=False
Echo Output=False
Write Detailed=0

--- LITCOALRV.f01 (steady flow) ---

Flow Title=NFF Regression Equation
Program Version=4.10
Number of Profiles= 1
Profile Names=P100yr
River Rch & RM=LITCOALRV,Main            ,10148.8
34905.47
River Rch & RM=LITCOALRV,Main            ,82
 35176.7
Boundary for River Rch & Prof#=LITCOALRV,Main            , 1
Up Type= 0
Dn Type= 3
Dn Slope=0.0008
DSS Import GetInterval= 0
DSS Import GetPeak= 0
DSS Import FillOption= 0

--- LITCOALRV.g01 (geometry) ---

Geom Title=USGS 10m DEM
Program Version=4.10

River Reach=LITCOALRV       ,Main
Reach XY= 30
     1724919.891      434747.802     1725055.308      434957.872
     1725161.211      435192.247     1725342.943       435785.68
     1725429.748      436215.367     1725559.956      437319.968
     1725681.484      437684.552     1725759.609      437780.038
     1726117.248      438097.746     1726286.519      438184.552
     1726985.303      438392.885      1727356.57      438571.991
     1727445.373      438688.024     1727484.435      438931.079
     1727441.033      439113.371     1727371.588      439278.302
      1726928.88      439882.468     1726829.053        440069.1
     1726742.248      440346.878     1726733.567      440572.572
     1726768.289      440828.649     1726842.074      441102.086
     1726946.241      441310.419     1727180.616      441562.156
     1727443.637      441653.301     1727664.991      441644.621
     1728407.179      441510.072     1728710.998       441479.69
     1728875.929       441484.03     1729133.972      441565.798

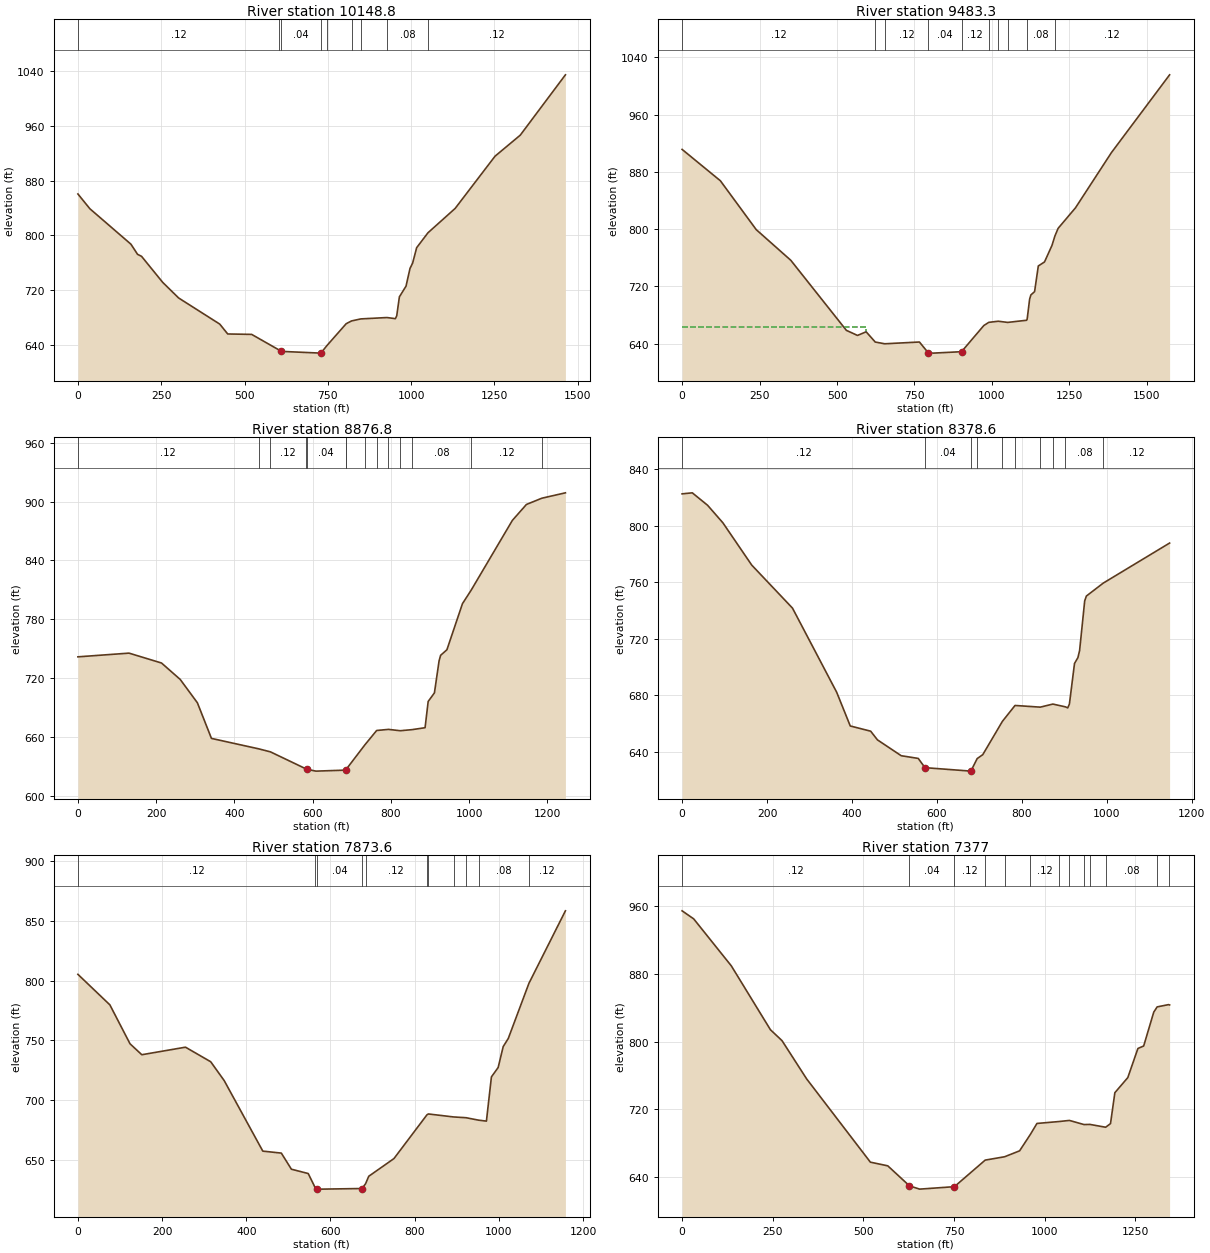
Type RM Length L Ch R = 1 ,10148.8 ,657.3,665.5,673.6
XS GIS Cut Line= 4
     1724409.474      435154.052     1724856.252      435038.572
     1725223.964       434776.77     1725751.488      434621.066
#Sta/Elev= 30
       0  860.39    35.8  838.85   159.1  787.03     179   772.2     191  769.26
   254.6  731.16   302.3  708.41   425.7  670.23   449.5  655.83   521.4  655.22
  603.45632.4805   609.3  630.41   729.1  627.84  747.08638.7869     805   670.8
  820.99 674.868  848.92677.8409  927.21679.8345   952.7  678.21   956.7  682.32
   964.7  710.09   984.6  725.68   996.6  751.71  1004.5   759.5  1016.5   781.9
 1050.39803.6602  1132.1  839.32  1251.6  915.54  1327.4  946.35  1462.9 1034.51
#Mann= 9 ,-1 , 0
       0     .12       0  603.45     .04       0   609.3     .04       0
   729.1     .04       0  747.08     .12       0  820.99     .08       0
  848.92    .016       0  927.21     .08       0 1050.39     .12       0
#XS Ineff= 2 , 0
       0   485.4                       0
Permanent Ineff=
       F       F
Bank Sta=609.3,729.1
XS Rating Curve= 0 ,0
Exp/Cntr=0.3,0.1

Type RM Length L Ch R = 1 ,9483.3  ,605.4,606.5,607.6
XS GIS Cut Line= 3
     1724458.863       435444.63     1725024.429      435598.098
     1725979.346      435347.282
#Sta/Elev= 30
       0  911.39   123.6  867.49   239.2  799.22   350.8  756.34   530.2  658.37
   566.1  651.28     594  656.36  623.34  642.04  653.88639.5955   765.9  642.08
   793.9   627.3   809.9  626.54   901.8  628.54   973.8  665.14  989.79 669.575
 1020.32671.1279 1050.86669.4876 1111.93672.5046  1113.6  673.97  1121.6  702.05
  1125.6  707.85  1137.6  712.53  1149.6   748.4  1169.6  754.02  1193.6  777.01
 1203.55 790.727  1213.6  801.03  1269.5  829.64  1385.5  906.85  1573.3 1015.63
#Mann= 10 ,-1 , 0
       0     .12       0  623.34     .06       0  653.88     .12       0
   793.9     .04       0   901.8     .12       0  989.79    .016       0
 1020.32     .06       0 1050.86    .016       0 1111.93     .08       0
 1203.55     .12       0
#XS Ineff= 2 , 0
          593.93  663.48
Permanent Ineff=
       F       F
Bank Sta=793.9,901.8
XS Rating Curve= 0 ,0
Exp/Cntr=0.3,0.1

Type RM Length L Ch R = 1 ,8876.8  ,495.9,498.1,500.4
XS GIS Cut Line= 3
     1724866.849       436377.79     1724983.111      436212.787
     1726005.387      435998.323
#Sta/Elev= 30
       0  741.88   130.6  745.66   213.8  735.59   261.6  718.86   305.5  695.09
   341.4  658.84  462.02648.2437  492.19645.1536  582.73627.9116   584.6  627.43
   608.5  625.53   684.2  626.54  685.93627.3574  733.62 652.239   763.8 666.906
  793.97668.0217  824.15666.6551  854.33 667.764   887.6  669.73   895.5  696.45
   911.5  705.18   923.4  737.77   927.4  743.47   943.4  749.08   983.2  796.03
 1005.22809.6114  1110.8   880.8  1146.7  897.01 1186.29903.4003  1246.4  908.86
#Mann= 14 ,-1 , 0
       0     .12       0  462.02     .06       0  492.19     .12       0
  582.73     .04       0   584.6     .04       0   684.2     .04       0
  685.93     .12       0  733.62     .06       0   763.8    .016       0
  793.97     .06       0  824.15    .016       0  854.33     .08       0
 1005.22     .12       0 1186.29      .1       0
#XS Ineff= 2 , 0
       0   377.3                       0
Permanent Ineff=
       F       F
Bank Sta=584.6,684.2
XS Rating Curve= 0 ,0
Exp/Cntr=0.3,0.1

Type RM Length L Ch R = 1 ,8378.6  ,505.9,505,504.1
XS GIS Cut Line= 2
     1724842.193      436684.087     1725983.686      436562.559
#Sta/Elev= 30
       0  822.51      24  823.24      60  814.44      96  802.06     164  772.13
     260  741.68     364  682.21     396  658.36     444  654.68     460  648.54
     516  637.32     556  635.42     572  628.88     680  626.43   694.8  635.29
     708  638.08   754.2 661.618   783.9672.8625  843.31671.6786  873.01673.8447
  902.71671.8784     908  671.16     912  673.87     924  702.57     932  706.69
     936  711.72     948  746.84     952  750.26  991.82 759.423  1147.9  787.72
#Mann= 10 ,-1 , 0
       0     .12       0     572     .04       0     680     .04       0
   694.8     .12       0   754.2     .06       0   783.9    .016       0
  843.31     .06       0  873.01    .016       0  902.71     .08       0
  991.82     .12       0
Bank Sta=572,680
XS Rating Curve= 0 ,0
Exp/Cntr=0.3,0.1

Type RM Length L Ch R = 1 ,7873.6  ,500.7,496.6,492.6
XS GIS Cut Line= 2
     1724915.978      437209.261     1726061.811       437039.99
#Sta/Elev= 30
       0  805.19    75.9  779.72   123.8  747.19   151.8  738.04   255.6  744.34
   315.5  732.18   347.5  716.48   439.3  657.52   483.3  655.87   507.2  642.41
   547.2   638.8  564.09626.7487   567.2  626.01   579.1  625.77     675  626.28
  683.51630.2894     691   636.5   750.9  651.28  829.38687.8692  832.79688.5533
   892.5 686.068  922.36685.4186  952.21 683.361   970.6  682.58   982.5  719.52
   998.5  727.38  1010.5  744.86  1022.5  751.58 1071.64797.7143  1158.3  858.25
#Mann= 11 ,-1 , 0
       0     .12       0  564.09     .04       0   567.2     .04       0
     675     .04       0  683.51     .12       0  829.38     .06       0
  832.79    .016       0   892.5     .08       0  922.36    .016       0
  952.21     .08       0 1071.64     .12       0
Bank Sta=567.2,675
XS Rating Curve= 0 ,0
Exp/Cntr=0.3,0.1

Type RM Length L Ch R = 1 ,7377    ,560.4,547.3,534
XS GIS Cut Line= 3
     1725007.123        437816.9     1725960.665      437493.437
     1726207.995      437263.207
#Sta/Elev= 30
       0  954.56      32  945.04   135.8  889.49   243.7  813.98   275.7  801.07
   343.6  755.86   519.4  657.44   567.4   653.1   627.3   629.4   655.3  625.57
   751.2  628.47  836.09659.8672  889.73663.8409     931  670.83  960.84690.3162
   978.9  703.22 1038.36705.4174 1068.36 706.778 1108.71701.8979 1125.05702.0654
  1168.4 698.735  1181.8  703.01  1193.8  739.54  1229.5   757.4  1257.4  791.84
  1273.3  794.78  1301.1  834.81 1310.47840.9924 1341.79843.6713  1344.8  843.28
#Mann= 13 ,-1 , 0
       0     .12       0   627.3     .04       0   751.2     .12       0
  836.09    .016       0  889.73     .08       0  960.84     .12       0
 1038.36     .06       0 1068.36    .016       0 1108.71     .06       0
 1125.05    .016       0  1168.4     .08       0 1310.47     .12       0
 1341.79     .08       0
Bank Sta=627.3,751.2
XS Rating Curve= 0 ,0
Exp/Cntr=0.3,0.1

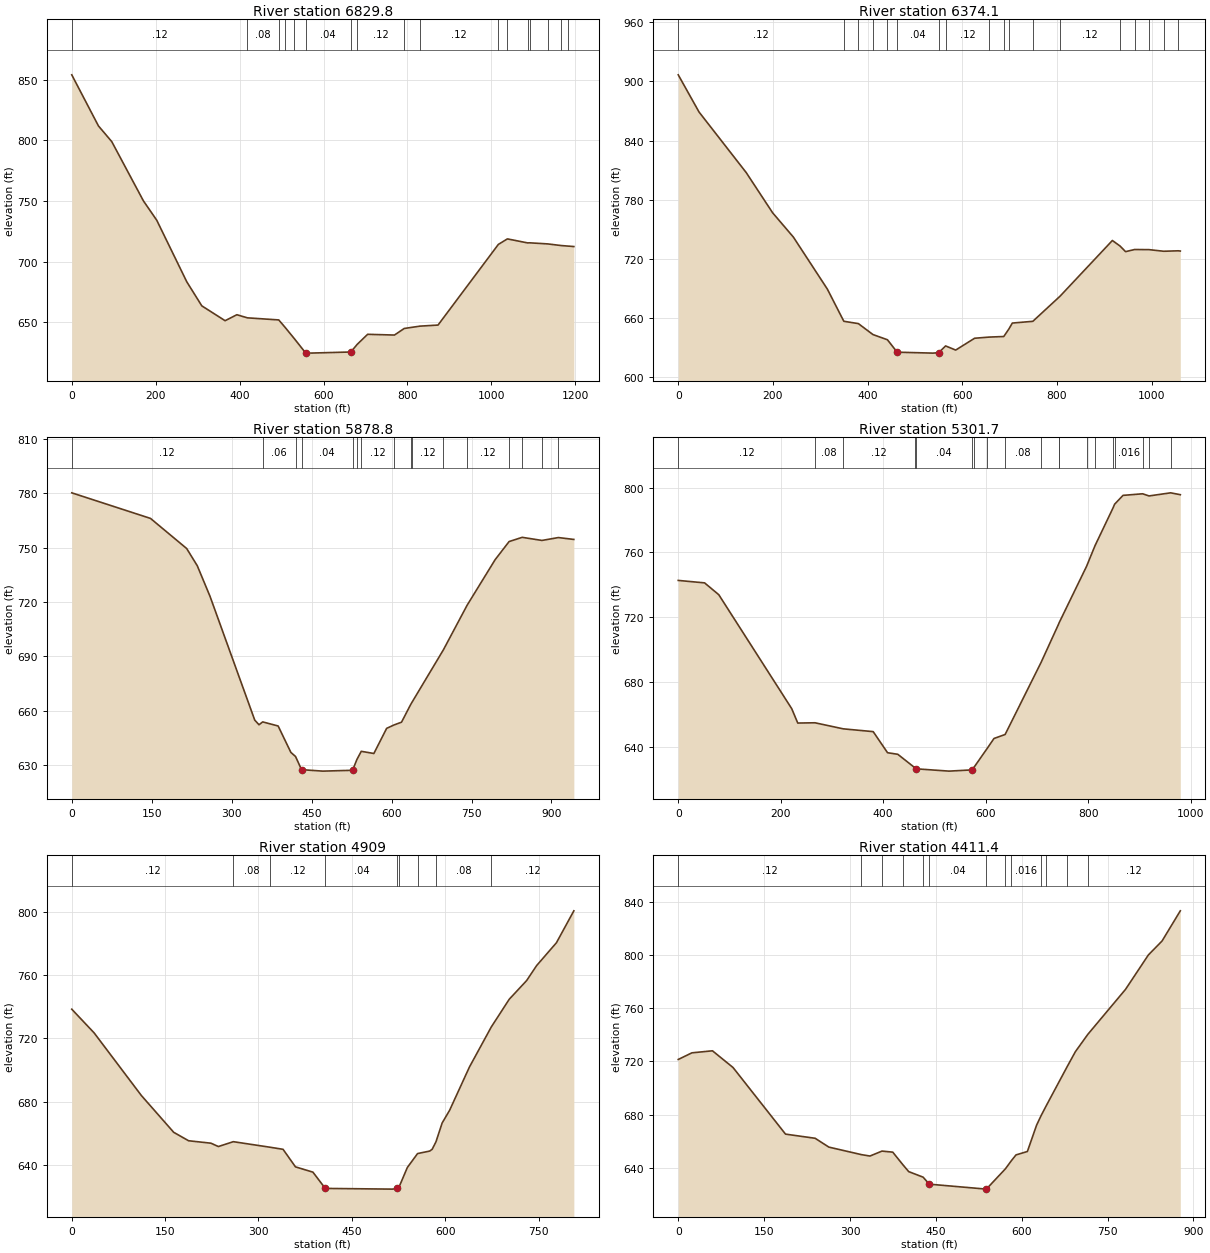
Type RM Length L Ch R = 1 ,6829.8  ,464.4,455.7,447.1
XS GIS Cut Line= 3
     1725826.051       438556.61     1725856.433      438196.367
     1726368.585      437536.644
#Sta/Elev= 30
       0  853.98    63.6  811.89    95.4  798.91   170.8  750.14   202.6  734.17
   274.1  683.51   309.9  663.68   365.5  651.43   393.5  656.35  418.55 653.794
  493.33652.0677  508.52645.9248  530.72636.5488   557.3  624.92   565.3  624.72
   665.2  625.65  680.28 631.918   705.2  640.22   769.1  639.61  792.45645.0322
  829.84 646.951     873  647.84 1016.79714.2831 1038.32718.8229 1086.48715.5222
 1091.57715.5877 1134.65714.6806 1166.36713.3444 1182.81 712.902  1196.7  712.53
#Mann= 17 ,-1 , 0
       0     .12       0  418.55     .08       0  493.33     .12       0
  508.52     .08       0  530.72     .04       0   557.3     .04       0
   665.2     .08       0  680.28     .12       0  792.45    .016       0
  829.84     .12       0 1016.79     .06       0 1038.32    .016       0
 1086.48     .06       0 1091.57    .016       0 1134.65     .08       0
 1166.36     .06       0 1182.81     .08       0
#XS Ineff= 2 , 0
       0   393.5                       0
Permanent Ineff=
       F       F
Bank Sta=557.3,665.2
XS Rating Curve= 0 ,0
Exp/Cntr=0.3,0.1

Type RM Length L Ch R = 1 ,6374.1  ,495,495.3,495.5
XS GIS Cut Line= 2
     1726257.123      438724.018     1726547.922      437704.052
#Sta/Elev= 30
       0  906.65    43.9  868.94   143.5  807.51   199.4  766.64   243.2  741.99
     315  689.21  349.82656.5299  380.53654.1689  411.25643.0817  441.96  637.76
   462.5  625.17   538.3  624.21   550.2   624.7  564.81631.5132   586.1  627.31
     626   639.3  656.94640.4896  687.65  641.07  698.62648.8156   705.7  654.72
  749.08656.4915  806.34681.8783   917.1  738.52  933.35732.8661     945  727.19
  964.06729.3606  994.78729.2303 1025.49727.5965  1056.2 728.048  1060.6  727.83
#Mann= 18 ,-1 , 0
       0     .12       0  349.82     .06       0  380.53     .08       0
  411.25     .12       0  441.96     .04       0   462.5     .04       0
   550.2     .08       0  564.81     .12       0  656.94     .06       0
  687.65     .12       0  698.62    .016       0  749.08     .08       0
  806.34     .12       0  933.35     .06       0  964.06    .016       0
  994.78     .06       0 1025.49    .016       0  1056.2     .08       0
#XS Ineff= 2 , 0
       0                   709.7       0
Permanent Ineff=
       F       F
Bank Sta=462.5,550.2
XS Rating Curve= 0 ,0
Exp/Cntr=0.3,0.1

Type RM Length L Ch R = 1 ,5878.8  ,570.9,577.1,583.3
XS GIS Cut Line= 2
     1726738.894      438819.504     1727007.992      437916.726
#Sta/Elev= 30
       0  780.16   147.7  766.06   215.6  749.46   235.5  739.96   259.5  723.03
   343.3  654.87   351.3  652.32  358.22653.8914   387.2  651.64   411.1  637.09
  419.86634.8158   431.1  627.56     471  626.76   526.9  627.22  534.91633.1281
  543.14637.6784   566.8  636.48   590.8  650.34  604.77652.2283   618.7  653.74
  635.59663.3116  638.31664.6921  697.23 693.612   741.7718.1685   794.3   743.3
  820.51753.2899   845.1755.6273  882.16753.9156  912.97755.5028     942  754.47
#Mann= 16 ,-1 , 0
       0     .12       0  358.22     .06       0  419.86     .04       0
   431.1     .04       0   526.9     .12       0  534.91     .08       0
  543.14     .12       0  604.77    .016       0  635.59     .08       0
  638.31     .12       0  697.23     .08       0   741.7     .12       0
  820.51     .06       0   845.1    .016       0  882.16     .06       0
  912.97    .016       0
#XS Ineff= 2 , 0
       0     363                       0
Permanent Ineff=
       F       F
Bank Sta=431.1,526.9
XS Rating Curve= 0 ,0
Exp/Cntr=0.3,0.1

Type RM Length L Ch R = 1 ,5301.7  ,368.1,392.7,417.4
XS GIS Cut Line= 3
     1726989.245       438877.79     1727267.023      438799.665
     1727640.287      438218.068
#Sta/Elev= 30
       0  742.66    51.4  741.14    79.1  733.84   221.4   663.5   233.2   654.6
  266.84654.7649  321.95651.0246   380.4   649.3   408.4  636.28   428.4  635.31
  462.33626.8374   464.3  626.34   528.2  624.92   572.2  625.66  577.94627.6702
   602.7 638.903   616.1  645.07   637.8 647.539  707.99692.0643  741.99715.5775
  743.08716.4635  796.68751.3416  813.27764.1619  848.37 787.429  851.36789.6789
   867.8  795.15  906.04796.1398  918.56 794.811  960.72 796.732   979.6  795.58
#Mann= 19 ,-1 , 0
       0     .12       0  266.84     .08       0  321.95     .12       0
  462.33     .04       0   464.3     .04       0   572.2     .08       0
  577.94     .12       0   602.7    .016       0   637.8     .08       0
  707.99     .12       0  741.99     .08       0  743.08     .12       0
  796.68     .08       0  813.27     .12       0  848.37     .06       0
  851.36    .016       0  906.04     .08       0  918.56    .016       0
  960.72     .08       0
#XS Ineff= 2 , 0
       0     265                       0
Permanent Ineff=
       F       F
Bank Sta=464.3,572.2
XS Rating Curve= 0 ,0
Exp/Cntr=0.3,0.1

Type RM Length L Ch R = 1 ,4909    ,485.4,497.6,509.7
XS GIS Cut Line= 2
     1727016.672      438949.712     1727821.553      439004.526
#Sta/Elev= 30
       0  738.56    35.9  723.56   111.8  683.89   163.8  660.56   187.7  655.22
   223.6  653.67   235.6  651.55  259.58654.6271  318.78651.0972   339.5  649.79
   359.4  638.68   387.4  635.34   407.4  625.02   515.2  624.57   523.2  625.14
  526.01626.0392   539.2  638.29  555.61647.0936   575.1  648.69   579.1  649.82
  585.22654.6175   595.1  666.47   607.1  674.52     639  701.97  674.03 727.285
   702.9  744.86   730.9  756.72   746.8  766.14   778.8   780.7   806.7  800.88
#Mann= 9 ,-1 , 0
       0     .12       0  259.58     .08       0  318.78     .12       0
   407.4     .04       0   523.2     .04       0  526.01     .12       0
  555.61    .016       0  585.22     .08       0  674.03     .12       0
#XS Ineff= 2 , 0
       0   267.6                       0
Permanent Ineff=
       F       F
Bank Sta=407.4,523.2
XS Rating Curve= 0 ,0
Exp/Cntr=0.3,0.1

Type RM Length L Ch R = 1 ,4411.4  ,486.4,484.5,482.6
XS GIS Cut Line= 2
     1726864.762      439149.365     1727586.035      439648.274
#Sta/Elev= 30
       0  721.52    23.9   726.5    59.8  728.02    95.7   715.5   187.4   665.5
   239.2  662.38   263.1  655.76  320.04650.1102   334.9  649.06  355.95652.7673
   374.7  651.98  391.87  642.82   402.6  637.36  427.78633.1967   438.5  627.95
   538.2  624.23  571.43 639.444  581.92645.5772     590  649.91   609.9  652.47
   625.9  672.18  633.84679.3744  643.25687.1434  679.16715.9675   693.6  727.28
  715.08740.1645   781.3  774.13   821.2  799.94   845.1  810.41     877  833.06
#Mann= 13 ,-1 , 0
       0     .12       0  320.04     .06       0  355.95     .08       0
  391.87     .12       0  427.78     .08       0   438.5     .04       0
   538.2     .04       0  571.43     .12       0  581.92    .016       0
  633.84     .08       0  643.25     .12       0  679.16     .08       0
  715.08     .12       0
#XS Ineff= 2 , 0
       0     366                       0
Permanent Ineff=
       F       F
Bank Sta=438.5,538.2
XS Rating Curve= 0 ,0
Exp/Cntr=0.3,0.1

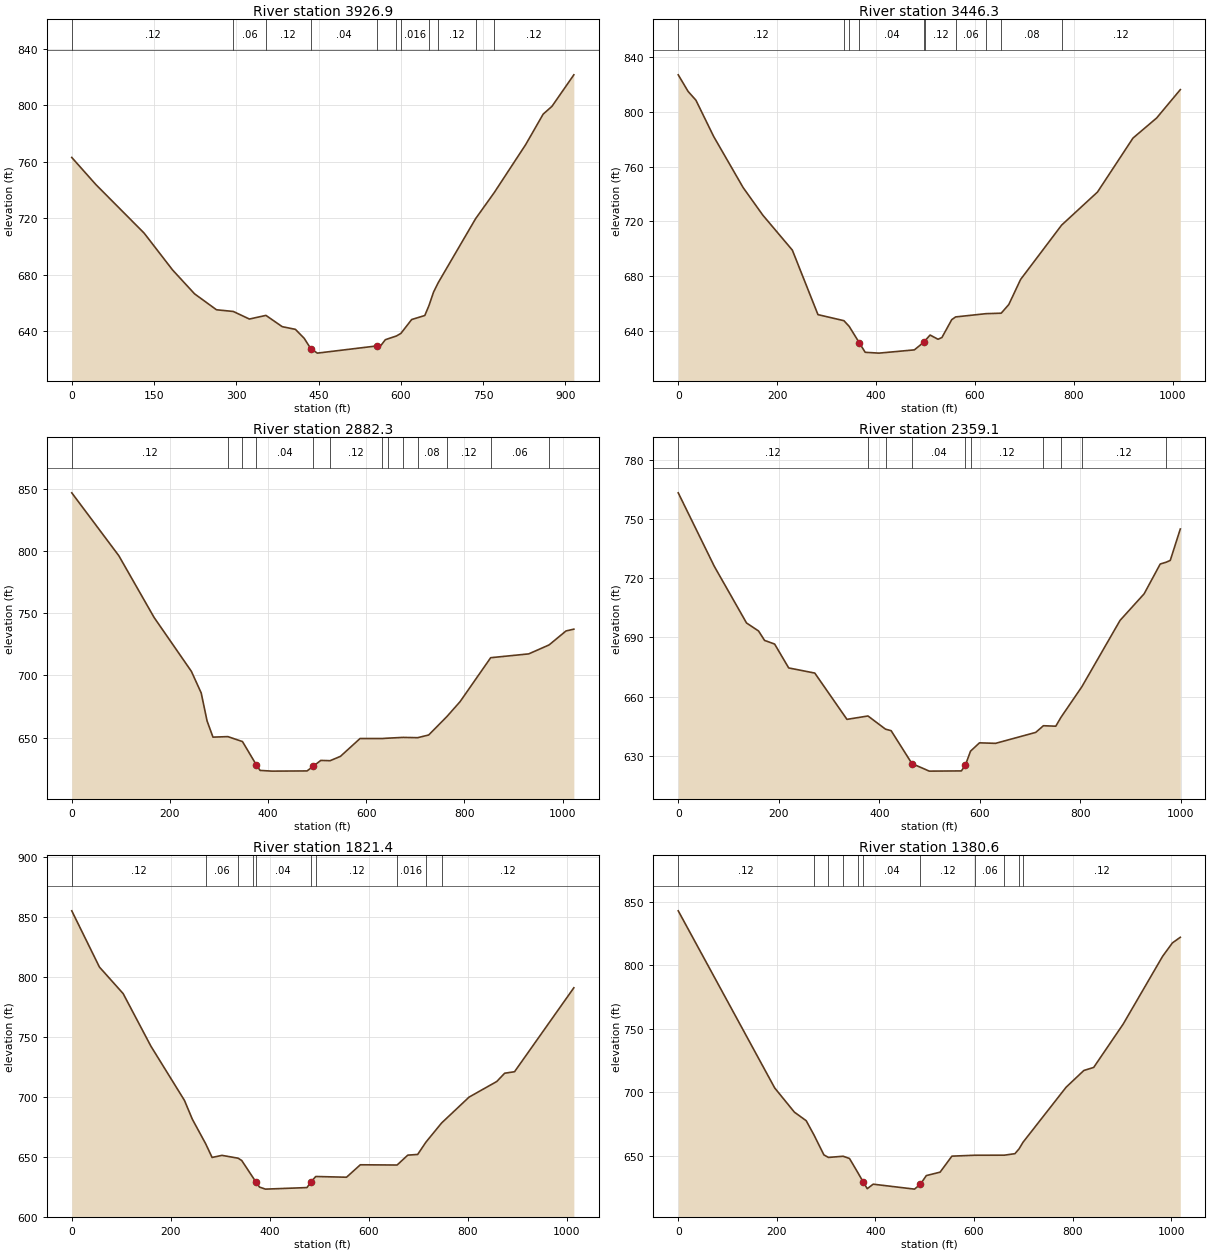
Type RM Length L Ch R = 1 ,3926.9  ,486,480.6,475.2
XS GIS Cut Line= 2
     1726547.922      439570.372     1727342.667      440025.102
#Sta/Elev= 30
       0  763.05      44   743.8     132  709.36   183.9  683.21   223.9  666.31
   263.9     655  294.62653.7896   323.9  648.42  354.09651.0052   383.8  643.01
   407.8  641.11   423.8  634.78   435.8  627.43   447.8  624.24   555.8  629.32
   559.8  627.66   571.8  633.76  591.98636.3816  600.23638.2467   619.8  648.06
   643.8  650.93  651.45658.0342   659.7  667.48  668.29674.2212  736.34719.5496
  770.37738.0882   827.7  772.13   859.7  793.81   875.7  799.32   915.6  821.67
#Mann= 11 ,-1 , 0
       0     .12       0  294.62     .06       0  354.09     .12       0
   435.8     .04       0   555.8     .04       0  591.98     .12       0
  600.23    .016       0  651.45     .08       0  668.29     .12       0
  736.34     .08       0  770.37     .12       0
Bank Sta=435.8,555.8
XS Rating Curve= 0 ,0
Exp/Cntr=0.3,0.1

Type RM Length L Ch R = 1 ,3446.3  ,573,564,554.9
XS GIS Cut Line= 3
      1726352.61      440125.927     1727060.075       440329.92
     1727333.512      440273.497
#Sta/Elev= 30
       0  827.11    19.9     815    35.8  808.54    71.6  782.06   131.3  744.62
   171.1  724.46   230.8  698.89   282.6   651.7  335.15647.2646  345.87643.0451
   366.2  631.13   378.1  624.15     406  623.54   477.6  625.92   497.5  631.77
  499.56632.7845   509.4  636.78   525.4  633.69   533.3  634.94   553.2  648.03
  561.04650.0215  622.52652.4058  653.25652.7504   668.6  659.09   692.5  677.45
  775.45 717.185     848  741.37   919.8  780.85   967.6  795.52  1015.5  816.28
#Mann= 10 ,-1 , 0
       0     .12       0  335.15     .08       0  345.87     .12       0
   366.2     .04       0   497.5     .04       0  499.56     .12       0
  561.04     .06       0  622.52    .016       0  653.25     .08       0
  775.45     .12       0
Bank Sta=366.2,497.5
XS Rating Curve= 0 ,0
Exp/Cntr=0.3,0.1

Type RM Length L Ch R = 1 ,2882.3  ,533.2,523.2,513.2
XS GIS Cut Line= 2
     1726339.589      440855.094     1727355.214      440733.566
#Sta/Elev= 30
       0  846.95    95.9  796.34   167.8  746.64   243.7  703.33   263.7  685.94
   275.7  663.38   287.7  650.41  318.07650.8165  347.81 646.835   375.6  628.37
   383.6  623.64   407.6  623.06   479.5  623.22   491.5  626.87   507.4  631.68
  526.29631.4438   547.4  634.95   587.4  649.31  632.45649.2886  645.27649.6033
  675.02650.1882  704.76649.9624   727.2  652.14  764.25666.9503   791.1  678.95
  853.49714.3092     931  717.38  972.48724.5911  1006.9  735.82  1022.9  737.28
#Mann= 13 ,-1 , 0
       0     .12       0  318.07     .08       0  347.81     .12       0
   375.6     .04       0   491.5     .04       0  526.29     .12       0
  632.45     .06       0  645.27     .12       0  675.02    .016       0
  704.76     .08       0  764.25     .12       0  853.49     .06       0
  972.48     .12       0
Bank Sta=375.6,491.5
XS Rating Curve= 0 ,0
Exp/Cntr=0.3,0.1

Type RM Length L Ch R = 1 ,2359.1  ,552,537.7,523.4
XS GIS Cut Line= 2
       1726513.2      441562.559     1727358.368      441029.977
#Sta/Elev= 30
       0  763.16    71.9  725.89   135.9  697.28   159.8  693.24   171.8  688.46
   191.8  686.62   219.8  674.53   271.7  671.93   335.7   648.5  377.54650.2126
  412.45643.5309   423.6  642.77     465626.1275   499.5   622.3   563.4  622.41
   571.4  625.37  581.56 632.398   599.4  636.62   631.4  636.36   711.3   641.9
  726.64645.2795   751.2  645.04  761.55649.5322  803.15 665.031   879.1  698.59
     927  712.04     959  727.12  971.01728.0597     979  728.95     999  744.86
#Mann= 10 ,-1 , 0
       0     .12       0  377.54     .08       0  412.45     .12       0
     465     .04       0   571.4     .04       0  581.56     .12       0
  726.64    .016       0  761.55     .08       0  803.15     .12       0
  971.01     .08       0
#XS Ineff= 2 , 0
       0     367                       0
Permanent Ineff=
       F       F
Bank Sta=465,571.4
XS Rating Curve= 0 ,0
Exp/Cntr=0.3,0.1

Type RM Length L Ch R = 1 ,1821.4  ,452,440.8,429.7
XS GIS Cut Line= 2
     1727181.603       442035.65     1727554.633      441092.781
#Sta/Elev= 30
       0  855.34    55.9  808.42   103.8  786.27   159.7  742.51   227.6  697.17
   243.5  681.48  270.47660.9854   283.4  649.59   303.4  651.33  335.89 648.961
   343.3  647.03  365.76632.9909   371.3  629.52   379.2  624.85   391.2  623.16
     475  624.45     483  629.22  492.81633.6955   554.9  633.09   582.8  643.47
  657.03643.2678   678.6  651.51   698.6   652.1  715.15662.2974  746.91 678.335
   802.4  699.93   858.3  712.94   874.3  719.86   894.2   721.1    1014  791.14
#Mann= 10 ,-1 , 0
       0     .12       0  270.47     .06       0  335.89     .12       0
  365.76     .04       0   371.3     .04       0     483     .08       0
  492.81     .12       0  657.03    .016       0  715.15     .08       0
  746.91     .12       0
#XS Ineff= 2 , 0
       0     299                       0
Permanent Ineff=
       F       F
Bank Sta=371.3,483
XS Rating Curve= 0 ,0
Exp/Cntr=0.3,0.1

Type RM Length L Ch R = 1 ,1380.6  ,367.8,367.9,367.9
XS GIS Cut Line= 2
     1727828.304      442057.351     1727711.645      441045.678
#Sta/Elev= 30
       0  843.04   195.7  703.55   235.6  684.51   259.6  677.76  275.01666.7928
   295.5  650.84  304.74648.8388  334.47649.7877   347.4  648.01   364.2  636.97
   375.4  629.41   383.4  624.24   395.4  627.78   479.2  623.89   491.2   627.7
   503.2  634.55   531.2  637.26   555.1  649.87  602.05650.5736  661.51650.6242
   682.9   651.8  691.24655.5327  699.25 660.741   786.8  704.16   822.7  717.31
   842.7  719.73   902.6  753.91   982.4  807.18  1002.4   817.8  1018.4  822.21
#Mann= 11 ,-1 , 0
       0     .12       0  275.01     .06       0  304.74     .08       0
  334.47     .06       0   364.2     .04       0   375.4     .04       0
   491.2     .12       0  602.05     .06       0  661.51    .016       0
  691.24     .08       0  699.25     .12       0
#XS Ineff= 2 , 0
       0   327.5                       0
Permanent Ineff=
       F       F
Bank Sta=375.4,491.2
XS Rating Curve= 0 ,0
Exp/Cntr=0.3,0.1

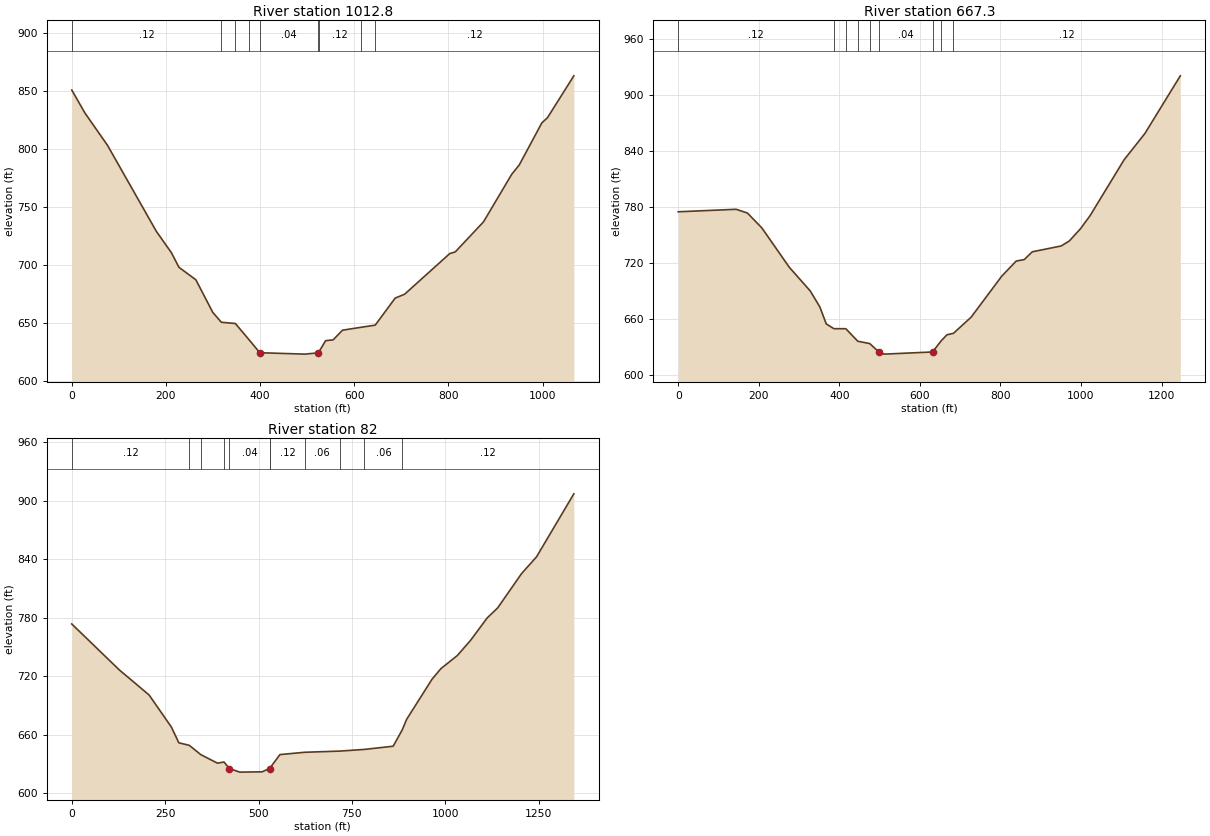
Type RM Length L Ch R = 1 ,1012.8  ,345.2,345.4,345.7
XS GIS Cut Line= 2
      1728190.53        442011.3     1728072.771      440951.471
#Sta/Elev= 30
       0  850.48      28  830.66    75.9  802.81   179.7  728.61   211.7  710.18
   227.6  697.64   263.6  686.86   299.5  658.77  317.69650.2456  347.41649.1788
  377.13634.8837   399.4  623.97   495.2  622.76   523.2  623.85  525.71 625.218
   539.2  634.36   555.1  635.05   575.1   643.4  614.86645.9353  644.58647.7775
   686.9  671.07   706.9   674.4   802.8  709.44   814.7  710.95   874.6  736.85
   934.6  777.91   950.5  785.92   998.5  822.21  1010.4  826.62  1066.4  862.73
#Mann= 9 ,-1 , 0
       0     .12       0  317.69     .08       0  347.41     .12       0
  377.13     .04       0   399.4     .04       0   523.2     .04       0
  525.71     .12       0  614.86    .016       0  644.58     .12       0
Bank Sta=399.4,523.2
XS Rating Curve= 0 ,0
Exp/Cntr=0.3,0.1

Type RM Length L Ch R = 1 ,667.3   ,576.2,585.3,594.5
XS GIS Cut Line= 2
     1728535.956      442050.553     1728410.347       440810.16
#Sta/Elev= 30
       0   774.6   143.8  777.27   171.8  773.26   207.8  757.26   275.7  715.21
   327.7  689.88   351.6  672.74   367.6   654.5   386.5 649.401  416.19 649.361
  445.88635.9441  475.56633.4701   499.5   623.9   511.5  622.15   631.4  624.46
  653.68 636.783   667.3  642.87  683.37644.4266   727.3  661.73   803.2  705.59
   839.2  721.82   859.1   723.4   879.1  731.74     951     738     971  743.31
     999  756.54    1023  770.67  1106.9  830.14  1158.8  858.46  1246.7   920.2
#Mann= 9 ,-1 , 0
       0     .12       0   386.5     .06       0  416.19     .08       0
  445.88     .12       0  475.56     .04       0   499.5     .04       0
   631.4     .12       0  653.68    .016       0  683.37     .12       0
Bank Sta=499.5,631.4
XS Rating Curve= 0 ,0
Exp/Cntr=0.3,0.1

Type RM Length L Ch R = 1 ,82      ,82,82,82.1
XS GIS Cut Line= 3
     1728912.784      441995.598       1729132.6      441296.896
     1728834.278      440763.057
#Sta/Elev= 30
       0  773.49   127.4  726.37     207  700.75   266.7  667.86   286.6  651.74
  314.54649.1596  345.51639.5957   390.1  630.87  407.43 632.077     422  625.37
   449.8  621.69   509.5  622.01   529.4  625.39  531.28626.3018   557.3  639.67
  624.17 642.043  717.05643.2227  783.29644.9578   860.4  648.24  884.79665.1121
   896.3  675.71   964.3  716.84   988.3  727.78  1032.2  741.19  1068.2  757.02
  1112.2  779.77  1140.2  789.99  1204.1  825.14  1244.1  842.27    1344  906.84
#Mann= 11 ,-1 , 0
       0     .12       0  314.54     .08       0  345.51     .12       0
  407.43     .04       0     422     .04       0   529.4     .04       0
  531.28     .12       0  624.17     .06       0  717.05    .016       0
  783.29     .06       0  884.79     .12       0
Bank Sta=422,529.4
XS Rating Curve= 0 ,0
Exp/Cntr=0.3,0.1

Chan Stop Cuts=-1
Use User Specified Reach Order=0
Composite Channel Slope=5